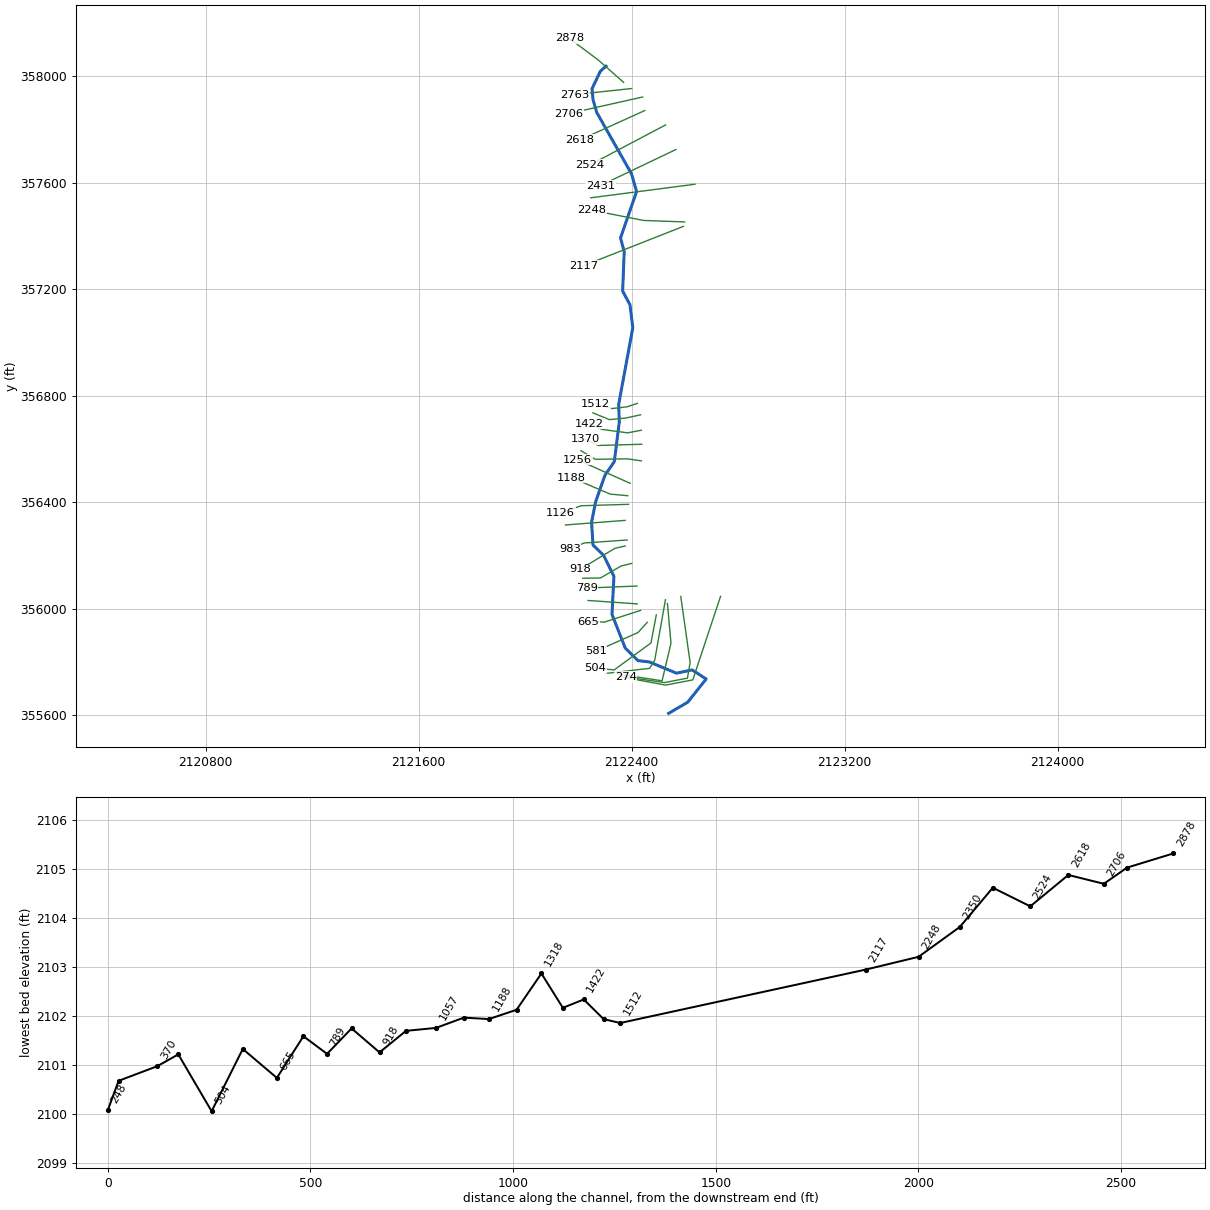
--- CLBRSNCKT3.prj (project) ---

Proj Title=CLBRSNCKT3
Current Plan=p02
Default Exp/Contr=0.3,0.1
English Units
Geom File=g01
Flow File=f01
Plan File=p01
Plan File=p02
Y Axis Title=Elevation
X Axis Title(PF)=Main Channel Distance
X Axis Title(XS)=Station
BEGIN DESCRIPTION:
Stream Name- Culberson Creek Tributary 3
Flood Zone: Zone A
Greenbrier County, WV
County-Wide Study
WVDHSEM-2018-3, Flood Risk Project
HEC-RAS Version: 5.0.7
General Notes:
For the Hydrology Regression was used.
END DESCRIPTION:
DSS Export Rating Curves= 0
DSS Export Rating Curve Sorted= 0
DSS Export Volume Flow Curves= 0
DXF Filename=CULBERSONTRIB.
DXF OffsetX= 0
DXF OffsetY= 0
DXF ScaleX= 1
DXF ScaleY= 10

--- CLBRSNCKT3.p02 (plan) ---

Plan Title=Floodplain
Program Version=5.07
Short Identifier=Floodplain
Geom File=g01
Flow File=f01
Subcritical Flow
K Sum by GR= 0
Std Step Tol= 0.01
Critical Tol= 0.01
Num of Std Step Trials= 20
Max Error Tol= 0.3
Flow Tol Ratio= 0.001
Split Flow NTrial= 30
Split Flow Tol= 0.02
Split Flow Ratio= 0.02
Log Output Level= 0
Friction Slope Method= 1
Unsteady Friction Slope Method= 2
Unsteady Bridges Friction Slope Method= 1
Parabolic Critical Depth
Global Vel Dist= 0 , 0 , 0
Global Log Level= 0
CheckData=True
Encroach Param=-1 ,0,0, 0
Computation Interval=1MIN
Output Interval=1HOUR
Instantaneous Interval=1HOUR
Mapping Interval=1HOUR
Computation Time Step Use Courant=        0
Computation Time Step Use Time Series=    0
Computation Time Step Count To Double=0
Computation Time Step Max Doubling=0
Computation Time Step Max Halving=0
Computation Time Step Residence Courant=0
Run HTab= 0
Run UNet= 0
Run Sediment= 0
Run PostProcess= 0
Run WQNet= 0
Run RASMapper=-1
UNET Theta= 1
UNET Theta Warmup= 1
UNET ZTol= 0.02
UNET ZSATol= 0.02
UNET MxIter= 20
UNET Max Iter WO Improvement= 0
UNET MaxInSteps= 0
UNET DtIC= 0
UNET DtMin= 0
UNET MaxCRTS= 20
UNET WFStab= 2
UNET SFStab= 1
UNET WFX= 1
UNET SFX= 1
UNET 1D Methodology=Finite Difference
UNET DSS MLevel= 4
UNET Pardiso=0
UNET DZMax Abort= 100
UNET Use Existing IB Tables=-1
UNET Froude Reduction=False
UNET Froude Limit= 0.8
UNET Froude Power= 4
UNET D1 Cores= 0
UNET D2 Coriolis=0
UNET D2 Cores= 0
UNET D2 Theta= 1
UNET D2 Theta Warmup= 1
UNET D2 Z Tol= 0.01
UNET D2 Volume Tol= 0.01
UNET D2 Max Iterations= 20
UNET D2 Equation= 0
UNET D2 RampUpFraction=0.1
UNET D2 TimeSlices= 1
UNET D2 BCVolumeCheck=0
UNET D1D2 MaxIter= 0
UNET D1D2 ZTol=0.01
UNET D1D2 QTol=0.1
UNET D1D2 MinQTol=1
Write IC File= 0
Write IC File at Fixed DateTime=0
Write IC File at Sim End=0
Echo Input=False
Echo Parameters=False
Echo Output=False
Write Detailed= 0
HDF Write Warmup=0
HDF Write Time Slices=0
HDF Flush=0
HDF Face Node Velocities=0
HDF Compression= 1
HDF Chunk Size= 1
HDF Spatial Parts= 1
HDF Use Max Rows=0
HDF Fixed Rows= 1
Calibration Method= 0
Calibration Iterations= 20
Calibration Max Change=0.05
Calibration Tolerance=0.2
Calibration Maximum=1.5
Calibration Minimum=0.5
Calibration Optimization Method= 1
WQ AD Non Conservative
WQ ULTIMATE=-1
WQ Max Comp Step=1HOUR
WQ Output Interval=15MIN
WQ Output Selected Increments= 0
WQ Output face flow=0
WQ Output face velocity=0
WQ Output face area=0
WQ Output face dispersion=0
WQ Output cell volume=0
WQ Output cell surface area=0
WQ Output cell continuity=0
WQ Output cumulative cell continuity=0
WQ Output face conc=0
WQ Output face dconc_dx=0
WQ Output face courant=0
WQ Output face peclet=0
WQ Output face adv mass=0
WQ Output face disp mass=0
WQ Output cell mass=0
WQ Output cell source sink temp=0
WQ Output nsm pathways=0
WQ Output nsm derived pathways=0
WQ Output MaxMinRange=-1
WQ Daily Max Min Mean=-1
WQ Daily Range=0
WQ Daily Time=0
WQ Create Restart=0
WQ Fixed Restart=0
WQ System Summary=0
WQ Write To DSS=0
WQ Use Fixed Temperature=0
Sorting and Armoring Iterations= 10
XS Update Threshold= 0.02
Bed Roughness Predictor= 0
Hydraulics Update Threshold= 0.02
Energy Slope Method= 1
Volume Change Method= 1
Sediment Retention Method= 0
XS Weighting Method= 0
Number of US Weighted Cross Sections= 1
Number of DS Weighted Cross Sections= 1
Upstream XS Weight=0
Main XS Weight=1
Downstream XS Weight=0
Number of DS XS's Weighted with US Boundary= 1
Upstream Boundary Weight= 1
Weight of XSs Associated with US Boundary= 0
Number of US XS's Weighted with DS Boundary= 1
Downstream Boundary Weight= 0.5
Weight of XSs Associated with DS Boundary= 0.5
Percentile Method= 0
Sediment Output Level= 3
Mass or Volume Output= 0
Output Increment Type= 1
Profile and TS Output Increment= 1
XS Output Flag= 0
XS Output Increment= 10
Write Gradation File= 0
Read Gradation Hotstart= 0
Write HDF5 File= 1
Write Binary Output= 1
Write DSS Sediment File= 0
SV Curve= 0
Specific Gage Flag= 0

--- CLBRSNCKT3.p01 (plan) ---

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Plan Title=CULBERSONTRIB
Short Identifier=fp
Geom File=g01
Run RASMapper= 0

--- CLBRSNCKT3.f01 (steady flow) ---

Flow Title=Flow
Program Version=5.07
Number of Profiles= 6
Profile Names=f1p,f10p,f4p,f2p,f02p,f1pplus
River Rch & RM=CULBERSONTRIB,Main            ,2878
     940     506     667     799    1301    1390
River Rch & RM=CULBERSONTRIB,Main            ,1512
     961     518     682     817    1329    1421
River Rch & RM=CULBERSONTRIB,Main            ,849
     965     520     685     820    1334    1427
River Rch & RM=CLBRSNCKT3,Main            ,2878
     940     506     667     799    1301    1390
River Rch & RM=CLBRSNCKT3,Main            ,1512
     961     518     682     817    1329    1421
River Rch & RM=CLBRSNCKT3,Main            ,849
     965     520     685     820    1334    1427
Boundary for River Rch & Prof#=CLBRSNCKT3,Main            , 1
Up Type= 0
Dn Type= 3
Dn Slope=0.0027
Boundary for River Rch & Prof#=CLBRSNCKT3,Main            , 2
Up Type= 0
Dn Type= 3
Dn Slope=0.0027
Boundary for River Rch & Prof#=CLBRSNCKT3,Main            , 3
Up Type= 0
Dn Type= 3
Dn Slope=0.0027
Boundary for River Rch & Prof#=CLBRSNCKT3,Main            , 4
Up Type= 0
Dn Type= 3
Dn Slope=0.0027
Boundary for River Rch & Prof#=CLBRSNCKT3,Main            , 5
Up Type= 0
Dn Type= 3
Dn Slope=0.0027
Boundary for River Rch & Prof#=CLBRSNCKT3,Main            , 6
Up Type= 0
Dn Type= 3
Dn Slope=0.0027
DSS Import GetInterval= 0
DSS Import GetPeak= 0
DSS Import FillOption= 0

--- CLBRSNCKT3.g01 (geometry) ---

Geom Title=Geometry
Program Version=5.07

River Reach=CLBRSNCKT3      ,Main
Reach XY= 30
2122303.74013497 358037.723710522122282.44386692358018.311718861
2122251.47334879357953.0868864722122255.46573505357910.917306566
2122269.18956283357863.7572438312122399.94021296357632.947412982
2122418.65452357357566.8235154962122358.42378918357392.910414177
2122372.21041638357340.5810475552122366.32047194357193.332436706
 2122393.8068793357142.2862516122122404.60511077357055.900399914
2122351.59561086356768.2747800552122353.76495467356700.415773153
2122334.98970596356552.5423377312122300.03612642356501.709265843
2122265.26763631356403.1246310922122249.73372592 356325.47817111
2122254.99032259 356239.704160022122295.03198293356200.543505207
2122333.63156667356122.0244369512122326.42222343355978.864682913
2122376.16709623355852.4532117552122423.95757107355805.544127718
2122466.97832727355800.400588617 2122568.6494581355758.271666974
  2122627.120804 355770.694477352122680.06093353355736.500357881
2122610.62505126355649.2950690542122538.85303688355607.405277953

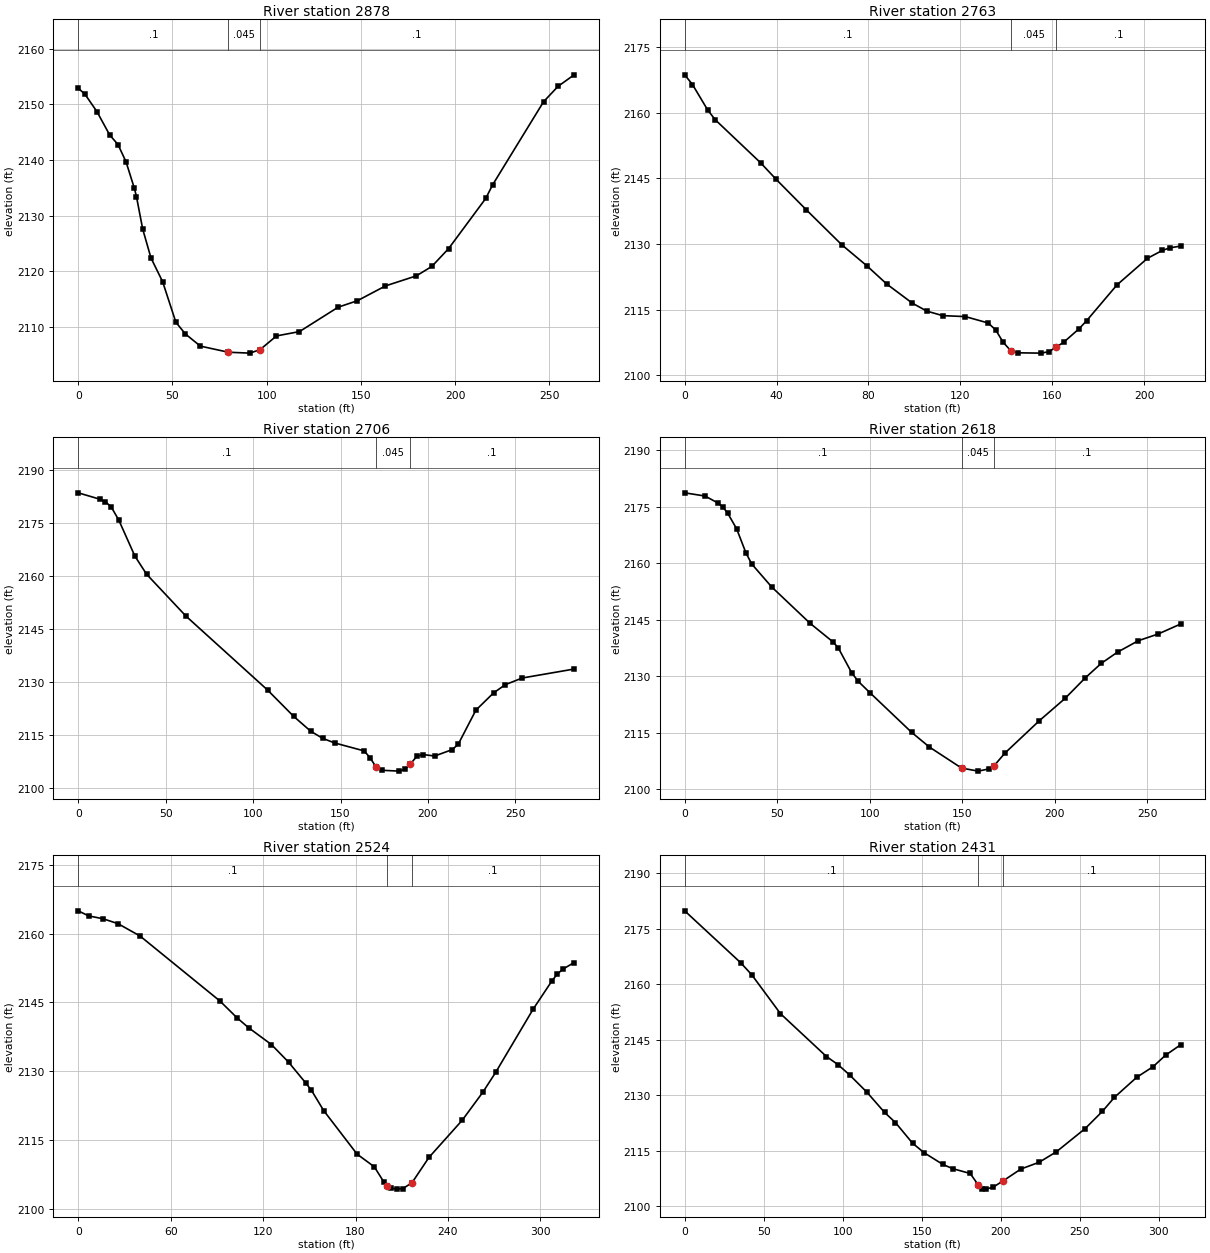
Type RM Length L Ch R = 1 ,2878    ,114.5,114.5,114.5
XS GIS Cut Line= 3
 2122370.0621772357976.8038124832122274.64507737358061.088917333
2122165.71055506358142.193452189
#Sta/Elev= 30
       0  2152.9     3.6 2151.81     9.9 2148.71    16.7  2144.5    21.1 2142.78
    25.4 2139.65    29.8  2134.9    30.9 2133.44    34.2 2127.61    38.6 2122.41
    44.8 2118.13    51.8 2110.87    56.8 2108.77    64.8 2106.57    79.7 2105.47
    91.1 2105.31    96.5 2105.94   105.2  2108.4   117.4 2109.18   137.9 2113.56
   148.1 2114.72     163 2117.38   179.4 2119.19   187.6 2120.88   196.5 2124.08
   216.2 2133.09   219.9 2135.56   246.9 2150.47   254.6 2153.24263.1234  2155.3
#Mann= 3 , 0 , 0
       0      .1       0    79.7    .045       0    96.5      .1       0
Bank Sta=79.7,96.5
XS Rating Curve= 0 ,0
Exp/Cntr(USF)=0,0
Exp/Cntr=0.3,0.1

Type RM Length L Ch R = 1 ,2763    ,57.2,57.2,57.2
XS GIS Cut Line= 2
2122400.27759214357953.7446800242122185.58911752357930.685547565
#Sta/Elev= 30
       0  2168.7     3.4 2166.48      10 2160.67    13.3 2158.42    33.1 2148.55
    39.7 2144.85    52.9 2137.84    68.4 2129.81    79.3 2125.01      88 2120.82
    99.1 2116.46   105.4 2114.64   112.3  2113.6   122.2 2113.38   132.1 2111.92
   135.4 2110.34   138.6 2107.55     142 2105.55   145.3 2105.09   155.2 2105.02
   158.5 2105.35   161.8 2106.41   165.1 2107.55   171.7 2110.59     175 2112.44
   188.2 2120.62   201.5 2126.72     208 2128.53   211.3 2129.12215.9233 2129.51
#Mann= 3 , 0 , 0
       0      .1       0     142    .045       0   161.8      .1       0
Bank Sta=142,161.8
XS Rating Curve= 0 ,0
Exp/Cntr(USF)=0,0
Exp/Cntr=0.3,0.1

Type RM Length L Ch R = 1 ,2706    ,87.6,87.6,87.6
XS GIS Cut Line= 2
2122441.62500207 357921.938980082122164.91541256 357859.91786519
#Sta/Elev= 30
       0 2183.53    12.2 2181.75    15.5 2181.04    18.9  2179.5    23.2 2175.81
    32.4 2165.61    39.1 2160.47    61.6 2148.61   108.3 2127.65   123.1 2120.25
     133 2115.97   139.9 2113.95   146.7 2112.66   163.5 2110.42   166.8 2108.54
   170.2 2105.94   173.6 2104.93   183.7 2104.69     187 2105.26   189.9  2106.7
   193.7 2108.92   197.1 2109.39   203.8 2108.97   213.9 2110.79   217.3 2112.32
   227.4 2121.97   237.5 2126.85   244.2 2129.18   253.9 2131.07283.5751 2133.61
#Mann= 3 , 0 , 0
       0      .1       0   170.2    .045       0   189.9      .1       0
Bank Sta=170.2,189.9
XS Rating Curve= 0 ,0
Exp/Cntr(USF)=0,0
Exp/Cntr=0.3,0.1

Type RM Length L Ch R = 1 ,2618    ,93.9,93.9,93.9
XS GIS Cut Line= 2
2122449.57642706357871.0498601712122205.46767999357760.525052867
#Sta/Elev= 30
       0 2178.71      11 2177.86    18.2 2175.95    20.7  2174.9    23.2 2173.34
    28.1 2169.13    33.1 2162.77    36.2 2159.85      47 2153.74    67.8 2144.07
    80.2 2139.13      83 2137.56    90.2    2131    93.8 2128.68     100 2125.72
   122.6 2115.17   132.2 2111.27   149.6 2105.68   158.6 2104.87   164.5 2105.47
     167 2106.19     173 2109.64   191.7 2118.28   205.5 2124.15   216.5 2129.64
   225.1 2133.47   233.9 2136.45   245.1 2139.47   255.9 2141.27267.9642  2143.9
#Mann= 3 , 0 , 0
       0      .1       0   149.6    .045       0     167      .1       0
Bank Sta=149.6,167
XS Rating Curve= 0 ,0
Exp/Cntr(USF)=0,0
Exp/Cntr=0.3,0.1

Type RM Length L Ch R = 1 ,2524    ,92.4,92.4,92.4
XS GIS Cut Line= 2
2122527.50039192357816.9801702672122242.83937742357666.698238034
#Sta/Elev= 30
       0 2164.98     6.7 2163.88    16.1 2163.25    25.8 2162.18    40.1 2159.49
      92 2145.29   103.1 2141.62   110.6 2139.46   125.4 2135.79   136.5 2131.96
   147.7 2127.39   151.4 2125.79   159.3 2121.39     181 2111.87   192.2  2109.1
   198.2 2105.88   200.6 2104.96     203 2104.41     207 2104.23   210.7 2104.36
   216.6  2105.6   227.7 2111.17   249.2 2119.25   262.7 2125.42     271 2129.74
   295.3 2143.53   307.4 2149.65   310.9 2151.16   314.7 2152.28321.8953 2153.69
#Mann= 3 , 0 , 0
       0      .1       0   200.6    .045       0   216.6      .1       0
Bank Sta=200.6,216.6
XS Rating Curve= 0 ,0
Exp/Cntr(USF)=0,0
Exp/Cntr=0.3,0.1

Type RM Length L Ch R = 1 ,2431    ,81.3,81.3,81.3
XS GIS Cut Line= 2
2122566.46237435357724.7436404312122283.39164485357589.569415671
#Sta/Elev= 30
       0 2179.83    35.4 2165.81    42.4 2162.56    60.6 2152.03    89.7 2140.44
    96.9 2138.29   104.3 2135.48   115.2 2130.84   126.4 2125.36   133.3 2122.61
   144.2 2116.99   151.5 2114.44   163.3 2111.28   169.7 2110.12   180.6 2108.84
   185.5 2105.85   187.9 2104.72   190.4 2104.61   195.1 2105.14   201.6 2106.89
   212.6 2110.03   224.2 2111.87   235.1  2114.7   253.3 2120.97   264.2 2125.62
   271.8 2129.41     286 2134.86   296.2 2137.68   304.2 2140.82313.6895 2143.62
#Mann= 3 , 0 , 0
       0      .1       0   185.5    .045       0   201.6      .1       0
Bank Sta=185.5,201.6
XS Rating Curve= 0 ,0
Exp/Cntr(USF)=0,0
Exp/Cntr=0.3,0.1

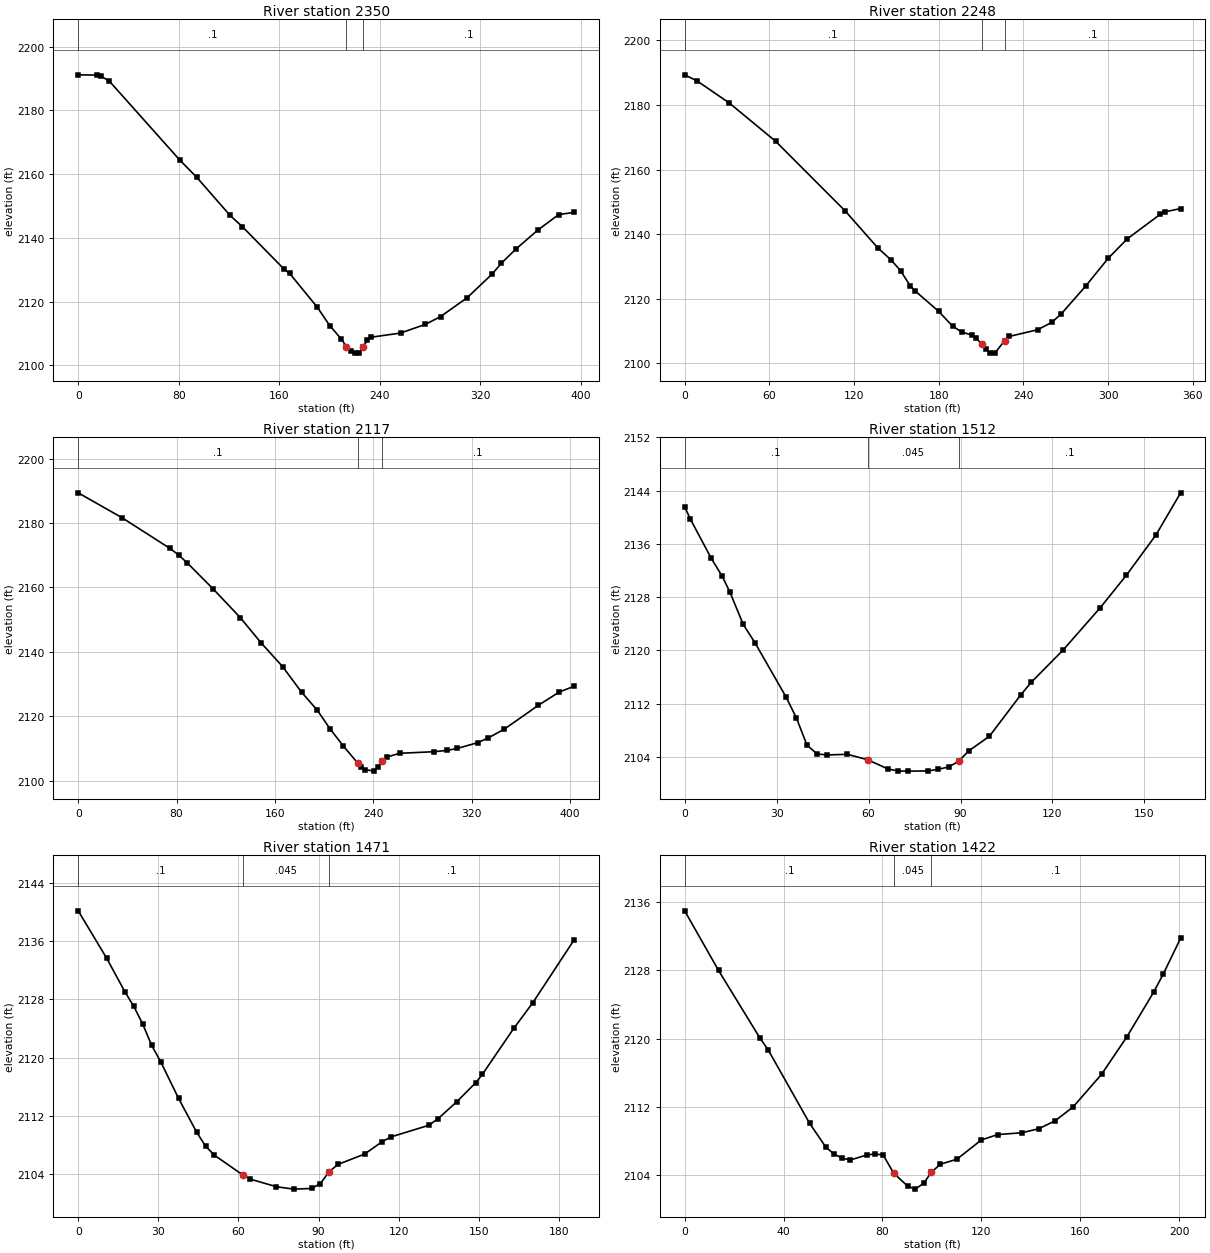
Type RM Length L Ch R = 1 ,2350    ,102,102,102
XS GIS Cut Line= 2
2122638.02519922357594.3402706622122246.81508992357543.451150753
#Sta/Elev= 30
       0 2191.19    14.8 2191.12    18.2 2190.76    24.8 2189.19      81 2164.34
    94.2 2159.05   120.7 2147.09   130.6 2143.51   163.7  2130.2   168.2 2128.82
   190.2 2118.21   200.1 2112.45   209.2 2108.26   213.4 2105.84   216.7 2104.36
     220 2103.81   223.3 2103.93   226.4 2105.68   229.9 2107.85   233.2 2108.82
   256.4 2110.11   276.2 2112.85   288.2 2115.27   309.3 2121.18   329.1 2128.57
   336.7 2132.07   348.1 2136.46   365.5 2142.41   382.1 2147.29394.5061 2148.02
#Mann= 3 , 0 , 0
       0      .1       0   213.4    .045       0   226.4      .1       0
Bank Sta=213.4,226.4
XS Rating Curve= 0 ,0
Exp/Cntr(USF)=0,0
Exp/Cntr=0.3,0.1

Type RM Length L Ch R = 1 ,2248    ,130.1,130.1,130.1
XS GIS Cut Line= 3
2122599.06321679357452.8049059142122444.80557206357458.370903404
2122251.58594491357496.537743336
#Sta/Elev= 30
       0 2189.35     8.8 2187.46    31.6 2180.63    64.4 2168.79   113.9 2147.12
   136.6 2135.87   146.5 2131.92     153 2128.66   159.7 2124.09   163.1 2122.51
   179.8 2116.18   189.8 2111.54   196.4  2109.7   203.2 2108.83   206.5  2107.9
   210.4 2105.94   213.2 2104.34   216.5  2103.2   219.9 2103.32   226.6 2107.03
   229.9 2108.37     250 2110.43     260 2112.72   266.7 2115.31     284 2123.93
   300.1 2132.59   313.5 2138.57   336.9 2146.18   340.3 2146.94351.3112 2147.95
#Mann= 3 , 0 , 0
       0      .1       0   210.4    .045       0   226.6      .1       0
Bank Sta=210.4,226.6
XS Rating Curve= 0 ,0
Exp/Cntr(USF)=0,0
Exp/Cntr=0.3,0.1

Type RM Length L Ch R = 1 ,2117    ,605.8,605.8,605.8
XS GIS Cut Line= 2
 2122594.2923618357436.1069134442122218.98510247357288.210408707
#Sta/Elev= 30
       0 2189.39    35.8 2181.62    74.6 2172.13    81.7 2170.06    88.7 2167.61
   109.9 2159.48   131.8 2150.64   148.7 2142.81   166.3 2135.39   181.8  2127.4
   194.5 2121.85   205.1 2115.93   215.7 2110.73   227.4 2105.41   229.8  2104.3
   233.3 2103.43   240.3 2102.94   243.9 2104.26   246.9 2106.01   250.9  2107.3
   261.5 2108.48   289.7 2108.98   300.3 2109.39   308.3 2109.99     325 2111.78
   333.6 2113.28   346.6 2115.98   374.3 2123.39   391.3 2127.52403.3967  2129.3
#Mann= 3 , 0 , 0
       0      .1       0   227.4    .045       0   246.9      .1       0
Bank Sta=227.4,246.9
XS Rating Curve= 0 ,0
Exp/Cntr(USF)=0,0
Exp/Cntr=0.3,0.1

Type RM Length L Ch R = 1 ,1512    ,40.9,41,40.6
XS GIS Cut Line= 4
2122421.62714998356771.3843593062122383.27406688356758.599998272
2122325.36843161356751.8318071372122265.20673263356770.632338068
#Sta/Elev= 30
       0 2141.58     1.8 2139.78     8.7 2133.81    12.2 2131.17    14.7 2128.82
    19.1  2123.9    22.9 2121.17      33 2113.05    36.4  2109.9    39.9 2105.76
    43.2 2104.43    46.5 2104.28    53.1 2104.38    59.7 2103.56    66.3 2102.18
    69.6 2101.87    72.9 2101.85    79.5 2101.88    82.8 2102.13    86.1 2102.48
    89.4 2103.33    92.7  2104.9    99.4 2107.08   109.7 2113.34   113.1 2115.22
   123.4 2120.02   135.5 2126.37   144.1 2131.29   153.8 2137.38   161.8 2143.68
#Mann= 3 , 0 , 0
       0      .1       0    59.7    .045       0    89.4      .1       0
Bank Sta=59.7,89.4
XS Rating Curve= 0 ,0
Exp/Cntr(USF)=0,0
Exp/Cntr=0.3,0.1

Type RM Length L Ch R = 1 ,1471    ,50.6,48.9,47.2
XS GIS Cut Line= 4
2122433.65948978356728.5191487812122378.76193946356716.486808985
2122316.34417677356710.4706390872122254.67843531356736.039361154
#Sta/Elev= 30
       0 2140.16    10.7 2133.62    17.5 2129.03    20.8 2127.04    24.2 2124.57
    27.5 2121.68    30.9 2119.42    37.6 2114.38    44.3 2109.78    47.7 2107.82
      51 2106.59    61.8 2103.83    64.3 2103.32    74.2 2102.26    80.8 2101.93
    87.4 2102.02    90.7  2102.7      94 2104.35    97.3 2105.33   107.2 2106.74
   113.8 2108.44   117.1  2109.1   131.2 2110.69   134.7 2111.59   141.8 2113.95
   148.9 2116.57   151.3 2117.68   163.1 2124.02   170.2 2127.52   185.7 2136.18
#Mann= 3 , 0 , 0
       0      .1       0    61.8    .045       0      94      .1       0
Bank Sta=61.8,94
XS Rating Curve= 0 ,0
Exp/Cntr(USF)=0,0
Exp/Cntr=0.3,0.1

Type RM Length L Ch R = 1 ,1422    ,50.3,51.6,52.8
XS GIS Cut Line= 4
2122436.66757473356670.6135135112122384.77810936356660.837237427
2122289.27141222 356673.621598462122242.64609551356695.430214341
#Sta/Elev= 30
       0 2134.99    13.7 2127.99    30.4 2120.08    33.8 2118.66    50.5 2110.07
    57.1 2107.25    60.4 2106.45    63.7 2105.97      67 2105.75    73.6 2106.33
      77 2106.47    80.3 2106.32    84.62104.179    90.2 2102.68    93.3 2102.33
    96.8 2103.05    99.72104.286   103.4 2105.25   110.1 2105.84     120  2108.1
   126.6 2108.73   136.5 2108.95   143.2 2109.42   149.8 2110.34   157.1 2111.97
   168.6  2115.8   178.8 2120.17   189.7 2125.45   193.5 2127.52   200.6 2131.78
#Mann= 3 , 0 , 0
       0      .1       0    84.6    .045       0    99.7      .1       0
Bank Sta=84.6,99.7
XS Rating Curve= 0 ,0
Exp/Cntr(USF)=0,0
Exp/Cntr=0.3,0.1

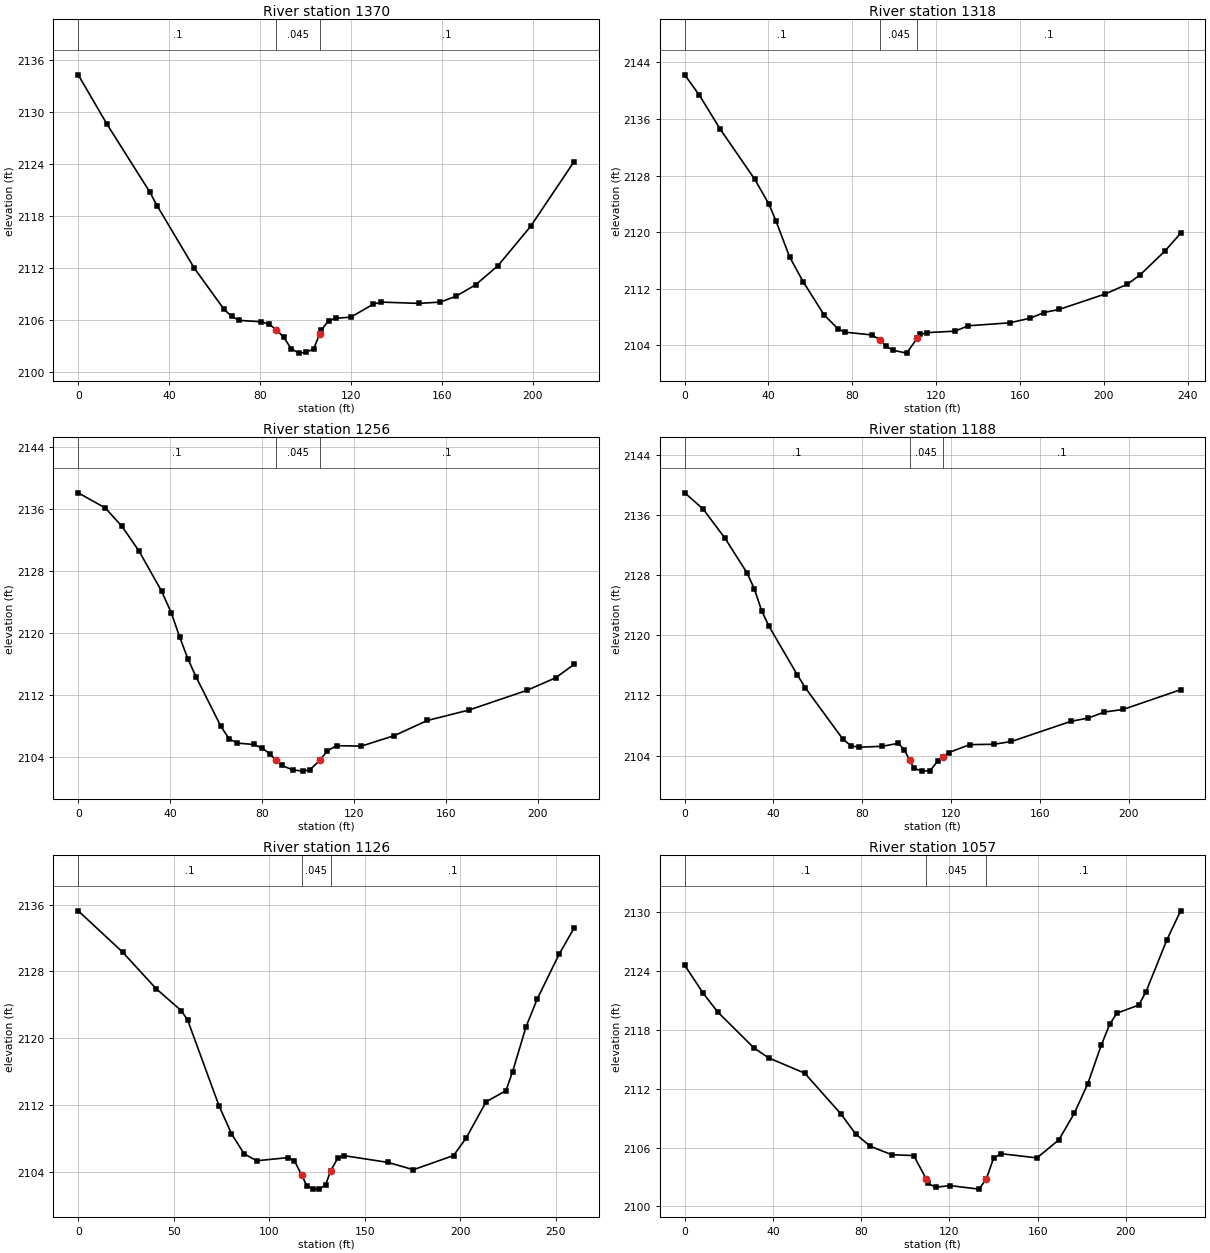
Type RM Length L Ch R = 1 ,1370    ,53.1,52.9,52.8
XS GIS Cut Line= 3
 2122438.1716172356617.9720269022122275.73502995356613.459899479
2122225.34960706356637.524579072
#Sta/Elev= 30
       0 2134.33    12.6 2128.65    31.4 2120.83    34.7 2119.21    51.1 2111.98
    64.2 2107.22    67.5 2106.42    70.8 2105.95    80.6 2105.78    83.9  2105.5
    87.2 2104.89    90.5 2103.97    93.8 2102.66    97.1 2102.16   100.3 2102.27
   103.6 2102.63   106.32104.389   106.9 2104.78   110.2 2105.92   113.5 2106.19
     120 2106.32   129.9 2107.82   133.2 2108.06   149.9 2107.91   159.4 2108.06
   166.4 2108.75     175 2110.07   184.8 2112.28   199.1  2116.8   218.3 2124.31
#Mann= 3 , 0 , 0
       0      .1       0    87.2    .045       0   106.3      .1       0
Bank Sta=87.2,106.3
XS Rating Curve= 0 ,0
Exp/Cntr(USF)=0,0
Exp/Cntr=0.3,0.1

Type RM Length L Ch R = 1 ,1318    ,64.6,61.3,58
XS GIS Cut Line= 4
2122436.66757473356555.5542642092122384.77810936356563.074476582
2122262.95066892356561.5704341072122209.55716107 356593.90734731
#Sta/Elev= 30
       0 2142.25       7 2139.38    16.9 2134.59    33.5 2127.44    40.2 2123.95
    43.5 2121.62    50.1 2116.46    56.7 2112.89    66.5 2108.29    73.1 2106.31
    76.4 2105.83    89.5 2105.43    93.12104.748    96.1 2103.84    99.3 2103.28
   105.9 2102.86   111.1 2105.01   112.5  2105.5   115.7 2105.76   128.9 2105.97
   135.4 2106.73   155.1 2107.15     165 2107.81   171.5 2108.61   178.7 2109.04
   200.5 2111.21   211.2  2112.6   217.3 2113.92   229.2  2117.3   236.7 2119.83
#Mann= 3 , 0 , 0
       0      .1       0    93.1    .045       0   111.1      .1       0
Bank Sta=93.1,111.1
XS Rating Curve= 0 ,0
Exp/Cntr(USF)=0,0
Exp/Cntr=0.3,0.1

Type RM Length L Ch R = 1 ,1256    ,68.3,68.4,68.6
XS GIS Cut Line= 2
2122394.55438544356471.3278856352122197.52482128356559.314370395
#Sta/Elev= 30
       0 2138.07    11.8 2136.11      19 2133.75    26.4 2130.58    36.3 2125.36
    40.5 2122.57    44.1 2119.48    47.7 2116.64    51.3 2114.28    62.1  2107.9
    65.7 2106.27    69.3 2105.74    76.4 2105.56      80 2105.11    83.5 2104.32
      86 2103.52    88.5 2102.86    93.4 2102.27      98 2102.12   100.9 2102.31
   105.32103.568   108.3 2104.71   112.4 2105.41   123.2 2105.35   137.5  2106.7
   151.9 2108.66   169.9    2110   195.3 2112.56   207.7 2114.17   215.8 2115.91
#Mann= 3 , 0 , 0
       0      .1       0      86    .045       0   105.3      .1       0
Bank Sta=86,105.3
XS Rating Curve= 0 ,0
Exp/Cntr(USF)=0,0
Exp/Cntr=0.3,0.1

Type RM Length L Ch R = 1 ,1188    ,58.3,61.6,64.8
XS GIS Cut Line= 3
 2122385.5301306356424.7025689242122320.10428295356430.718738822
2122174.96418416356492.384480278
#Sta/Elev= 30
       0 2138.92     8.3 2136.77    18.2 2132.87    28.1 2128.27    31.4 2126.14
    34.7 2123.23      38 2121.17    50.7 2114.74    54.4 2112.98    71.3 2106.17
    74.9  2105.3    78.5 2105.11      89 2105.23    96.3 2105.63      99 2104.71
   101.32103.411   103.4 2102.29     107 2101.93   110.6 2102.01   114.1 2103.31
   116.3 2103.86     119  2104.4   128.4 2105.45   139.3  2105.5   147.2 2105.87
     174 2108.55   181.9 2108.99     189 2109.78   197.5 2110.13   223.4 2112.75
#Mann= 3 , 0 , 0
       0      .1       0   101.3    .045       0   116.3      .1       0
Bank Sta=101.3,116.3
XS Rating Curve= 0 ,0
Exp/Cntr(USF)=0,0
Exp/Cntr=0.3,0.1

Type RM Length L Ch R = 1 ,1126    ,68.4,68.7,69.1
XS GIS Cut Line= 3
2122388.53821554356392.3656557212122211.06120355 356387.10150706
2122133.60301611356360.028742519
#Sta/Elev= 30
       0 2135.25    23.2 2130.32    40.8 2125.93      54  2123.3    57.3 2122.17
    73.7 2111.93    80.2  2108.6    86.8 2106.19    93.4 2105.35   109.8 2105.73
   113.1 2105.38     1172103.627   119.6 2102.39   122.9 2101.96   126.2 2101.96
   129.5 2102.47   132.12104.136     136 2105.71   139.3 2105.96   162.3 2105.15
   175.4 2104.28   196.5 2105.98   203.1 2108.09   213.5  2112.4   223.9 2113.74
   227.4 2116.03   234.4 2121.37   240.2 2124.67   251.7 2130.05   259.6  2133.2
#Mann= 3 , 0 , 0
       0      .1       0     117    .045       0   132.1      .1       0
Bank Sta=117,132.1
XS Rating Curve= 0 ,0
Exp/Cntr(USF)=0,0
Exp/Cntr=0.3,0.1

Type RM Length L Ch R = 1 ,1057    ,74.2,74.1,74.1
XS GIS Cut Line= 2
2122375.75385451 356332.20395674 2122151.6515258356314.907468282
#Sta/Elev= 30
       0 2124.62     8.4 2121.75      15 2119.83    31.4 2116.17      38 2115.16
    54.4 2113.59    70.9 2109.41    77.5 2107.38    84.1 2106.13    93.9 2105.26
   103.8 2105.18   109.4 2102.83   110.4 2102.33   113.7 2101.94   120.3 2102.11
   133.4 2101.75   136.7 2102.76     140  2104.9   143.3 2105.37   159.7 2104.94
   169.6 2106.78   176.6 2109.49   182.7  2112.5   188.8 2116.43   192.7 2118.61
   195.9 2119.72   205.8 2120.54   209.1  2121.9   218.5 2127.17   224.8 2130.17
#Mann= 3 , 0 , 0
       0      .1       0   109.4    .045       0   136.7      .1       0
Bank Sta=109.4,136.7
XS Rating Curve= 0 ,0
Exp/Cntr(USF)=0,0
Exp/Cntr=0.3,0.1

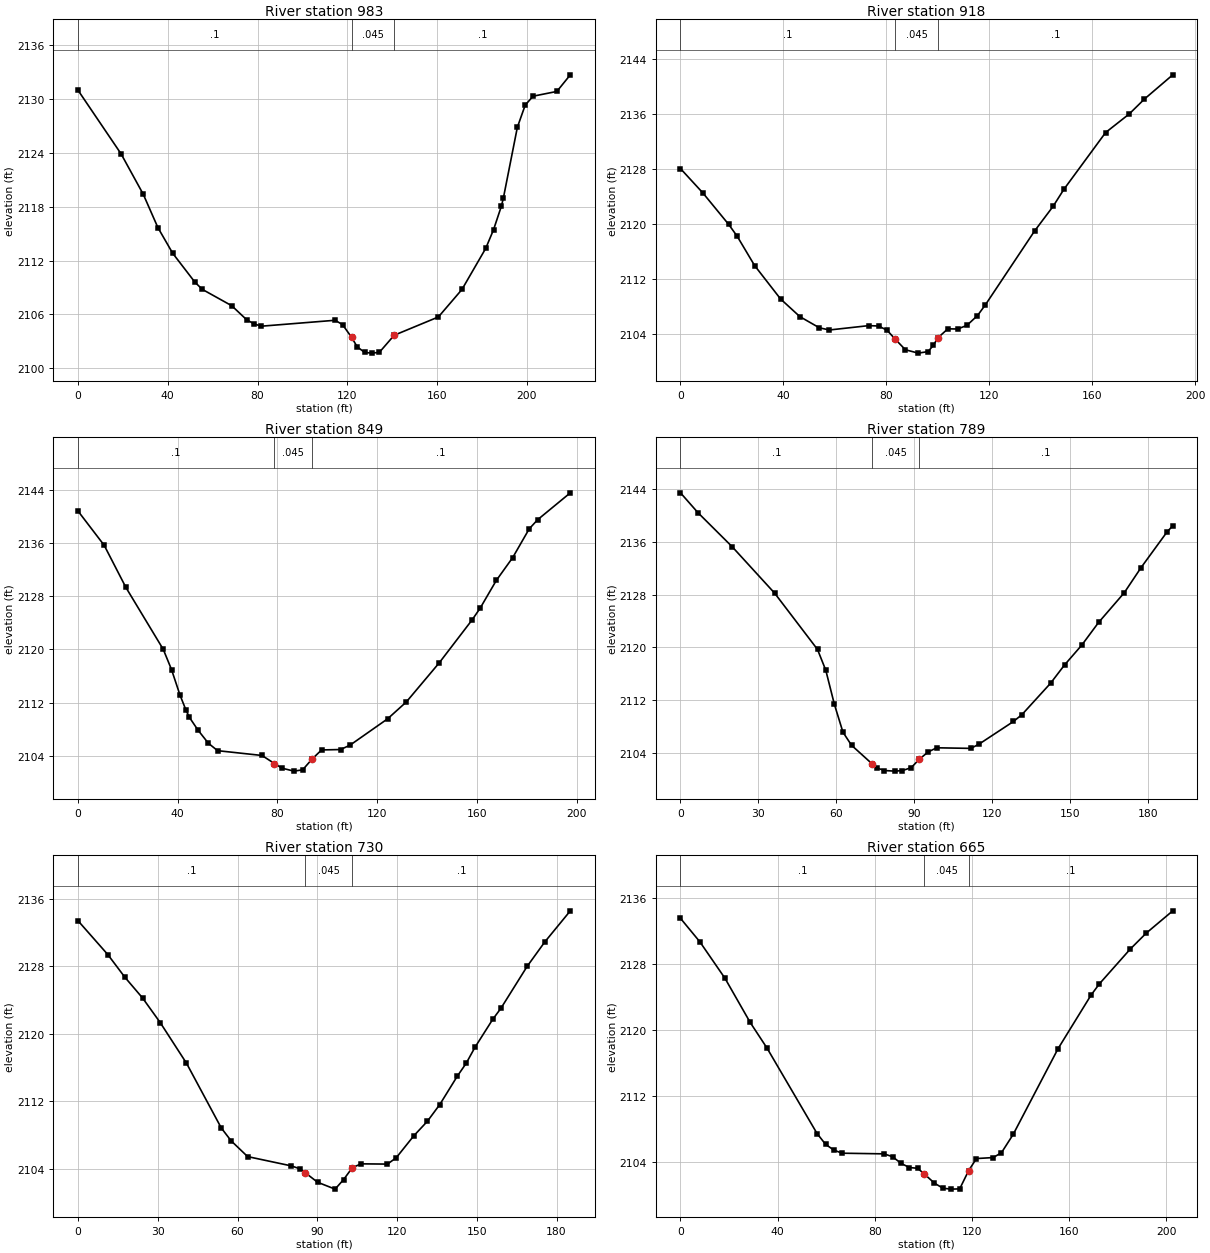
Type RM Length L Ch R = 1 ,983     ,61.5,65.2,68.9
XS GIS Cut Line= 3
2122383.27406688356258.5058754872122222.34152211356247.225556928
2122168.19599302356226.168962284
#Sta/Elev= 30
       0 2130.97    19.2 2123.88    29.1 2119.37    35.6 2115.67    42.2 2112.81
    52.1 2109.59    55.4 2108.79    68.5 2106.97    75.1 2105.42    78.4 2104.95
    81.7 2104.69   114.6 2105.35   117.9 2104.86   121.92103.457   124.4  2102.4
   127.7 2101.77     131 2101.69   134.3 2101.78   140.9 2103.68   160.6 2105.72
   171.1 2108.78   181.7 2113.36   185.2 2115.45   188.7 2118.08   189.6 2119.01
   195.8 2126.85   199.3 2129.32   202.8 2130.31   213.4 2130.84   219.4 2132.69
#Mann= 3 , 0 , 0
       0      .1       0   121.9    .045       0   140.9      .1       0
Bank Sta=121.9,140.9
XS Rating Curve= 0 ,0
Exp/Cntr(USF)=0,0
Exp/Cntr=0.3,0.1

Type RM Length L Ch R = 1 ,918     ,69.1,69,68.8
XS GIS Cut Line= 3
2122375.75385451356235.9452383692122336.64875017356226.920983522
2122207.30109736356148.710774845
#Sta/Elev= 30
       0 2128.11     8.6 2124.61    18.7    2120      22 2118.28    28.8    2114
    38.9 2109.13    46.4 2106.56      54 2104.93    57.9 2104.62    73.1 2105.25
      77  2105.2    80.3 2104.57    83.4  2103.3    87.4 2101.74    92.4 2101.25
    96.2 2101.47    98.3  2102.4     100 2103.47   103.9 2104.79   107.7 2104.76
   111.3 2105.29   115.4 2106.71   118.5 2108.29   137.6 2119.03   144.8 2122.62
     149  2125.1   165.2 2133.36   174.4 2136.07   180.3 2138.24   191.3 2141.76
#Mann= 3 , 0 , 0
       0      .1       0    83.4    .045       0     100      .1       0
Bank Sta=83.4,100
XS Rating Curve= 0 ,0
Exp/Cntr(USF)=0,0
Exp/Cntr=0.3,0.1

Type RM Length L Ch R = 1 ,849     ,64.1,60.5,56.8
XS GIS Cut Line= 4
2122400.57055534356170.5193907262122360.71342976356160.743114642
2122282.50322109356115.6218404052122216.32535221356114.869819168
#Sta/Elev= 30
       0 2140.77    10.5 2135.63    19.2 2129.31    34.2 2120.01    37.5 2116.99
    40.9 2113.16    43.3  2110.9    44.7  2109.8    48.1 2107.91    52.3 2105.92
      56 2104.81    73.8 2104.09    78.8 2102.88    81.8 2102.19    86.6 2101.74
    90.1 2101.93    93.9 2103.55    97.7 2104.92   105.3 2104.98   109.1 2105.63
   124.2 2109.59   131.7 2112.12   144.9 2117.99     158 2124.39   161.3 2126.18
   167.8 2130.36   174.4  2133.8     181  2138.1   184.4 2139.48   197.5 2143.51
#Mann= 3 , 0 , 0
       0      .1       0    78.8    .045       0    93.9      .1       0
Bank Sta=78.8,93.9
XS Rating Curve= 0 ,0
Exp/Cntr(USF)=0,0
Exp/Cntr=0.3,0.1

Type RM Length L Ch R = 1 ,789     ,59.1,58.3,57.5
XS GIS Cut Line= 2
2122420.12310751356085.5409909152122230.61375572356078.020778542
#Sta/Elev= 30
       0 2143.44     6.8  2140.4    19.9 2135.27    36.3 2128.21    52.8 2119.68
      56 2116.51    59.3 2111.36    62.6 2107.13    65.9 2105.15    73.92102.302
    75.7  2101.7    78.6 2101.31    82.6 2101.22    85.5  2101.3    88.9 2101.75
      92 2103.01    95.4 2104.12    98.7 2104.76   111.9 2104.67   115.1 2105.33
   128.3 2108.75   131.6  2109.8   142.6 2114.55     148 2117.33   154.6 2120.32
   161.1 2123.77     171 2128.28   177.5 2132.11   187.4 2137.46   189.7 2138.45
#Mann= 3 , 0 , 0
       0      .1       0    73.9    .045       0      92      .1       0
Bank Sta=73.9,92
XS Rating Curve= 0 ,0
Exp/Cntr(USF)=0,0
Exp/Cntr=0.3,0.1

Type RM Length L Ch R = 1 ,730     ,62.7,65.5,68.4
XS GIS Cut Line= 2
2122421.17593724356018.5358986742122236.40431924356031.395461831
#Sta/Elev= 30
       0 2133.42    11.2 2129.41    17.6 2126.73    24.3 2124.25    30.9 2121.35
    40.8 2116.52    53.9 2108.83    57.6 2107.31    63.8 2105.44    80.2 2104.34
    83.5 2103.99    85.52103.523    90.1  2102.4    96.7 2101.58    99.9 2102.71
   103.2 2104.13   106.5 2104.58   116.4 2104.55   119.7  2105.3   126.3  2107.9
   131.4 2109.62   136.1 2111.62   142.7 2114.99     146  2116.5   149.3 2118.39
     156 2121.72   159.1 2123.04     169 2128.03   175.6 2130.91   185.2  2134.6
#Mann= 3 , 0 , 0
       0      .1       0    85.5    .045       0   103.2      .1       0
Bank Sta=85.5,103.2
XS Rating Curve= 0 ,0
Exp/Cntr(USF)=0,0
Exp/Cntr=0.3,0.1

Type RM Length L Ch R = 1 ,665     ,83.3,84.1,84.9
XS GIS Cut Line= 3
 2122434.0355004355994.1704105862122297.99485858355950.177168206
2122238.43477658355952.207625546
#Sta/Elev= 30
       0 2133.59       8 2130.73    18.3 2126.32    28.7 2120.95    35.6 2117.85
    56.2 2107.48    59.7 2106.17    63.1 2105.47    66.5 2105.09    83.8 2105.01
    87.3 2104.66    90.7 2103.87    94.2 2103.35    97.6 2103.26   100.4 2102.55
   104.5 2101.46     108 2100.84   111.4 2100.73   114.9 2100.76   118.6 2102.98
   121.8 2104.44   128.7 2104.56   132.1 2105.15   136.9 2107.36   155.4 2117.78
     169 2124.29   172.4 2125.64   185.1 2129.86   191.7  2131.8   202.6  2134.5
#Mann= 3 , 0 , 0
       0      .1       0   100.4    .045       0   118.6      .1       0
Bank Sta=100.4,118.6
XS Rating Curve= 0 ,0
Exp/Cntr(USF)=0,0
Exp/Cntr=0.3,0.1

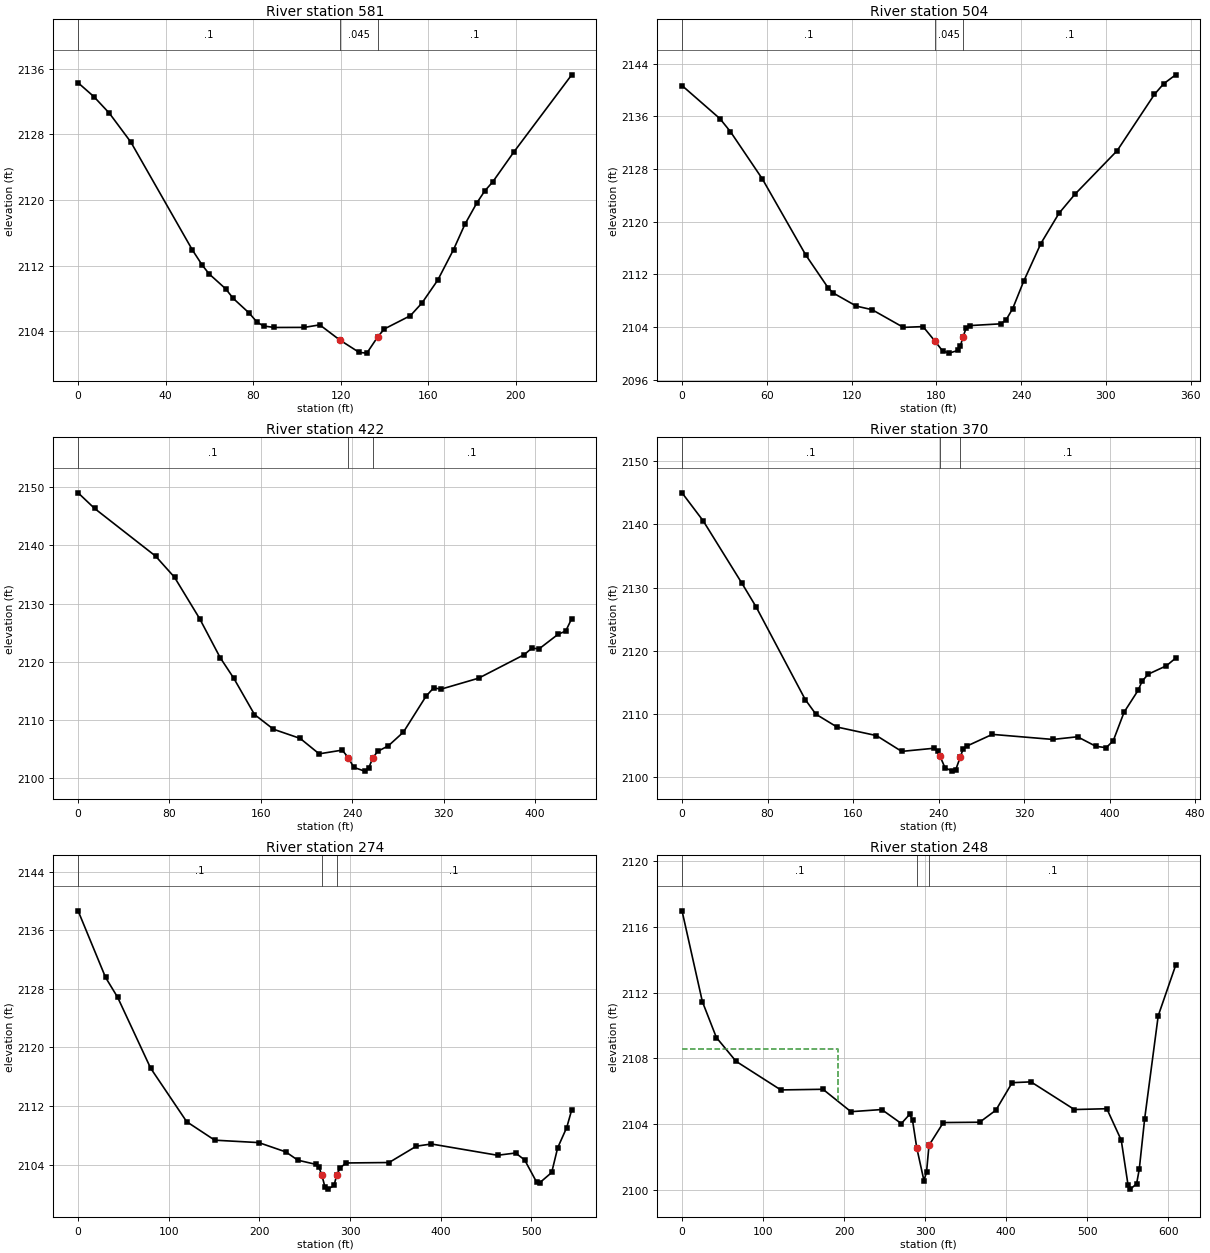
Type RM Length L Ch R = 1 ,581     ,75.3,76.9,78.6
XS GIS Cut Line= 3
 2122459.0778076355949.500349092 2122423.8832137 355910.92165962
2122265.50754113355840.532471812
#Sta/Elev= 30
       0 2134.31     7.2 2132.62    14.3 2130.59    24.1 2127.07    52.2 2113.91
    56.6  2112.1    59.8    2111    67.4 2109.17    70.9 2107.99    78.1 2106.22
    81.7 2105.12    84.7 2104.63    89.7 2104.45   103.3 2104.46   110.4 2104.77
   119.5 2102.93   128.4 2101.41   131.9 2101.32   136.9 2103.31   139.9 2104.27
   151.8 2105.89   157.1 2107.44   164.3 2110.23   171.5 2113.95   176.7 2117.04
   182.2 2119.67   185.8 2121.12   189.4 2122.21     199 2125.84   225.5 2135.28
#Mann= 3 , 0 , 0
       0      .1       0   119.5    .045       0   136.9      .1       0
Bank Sta=119.5,136.9
XS Rating Curve= 0 ,0
Exp/Cntr(USF)=0,0
Exp/Cntr=0.3,0.1

Type RM Length L Ch R = 1 ,504     ,79.4,82.2,85.1
XS GIS Cut Line= 4
2122492.76835903355977.0828169172122472.71445937355871.799843699
 2122334.8438992355770.6947662442122263.81967124355776.543820311
#Sta/Elev= 30
       0 2140.69    26.8 2135.67    34.3 2133.68    56.8 2126.53    87.6 2114.95
   103.6 2109.91   107.2 2109.16   123.4 2107.19   134.5 2106.65   156.7 2103.96
   170.6 2104.08   178.9 2101.91   184.4 2100.39     189 2100.05   195.5 2100.47
   197.1 2101.17   198.8 2102.47   201.1 2103.84   203.5 2104.23   225.6  2104.5
   229.3 2105.08     234 2106.78   241.8 2110.95     254  2116.7   266.8 2121.28
   278.1 2124.18     308  2130.8   334.4 2139.35   340.9 2140.96   349.4 2142.32
#Mann= 3 , 0 , 0
       0      .1       0   178.9    .045       0   198.8      .1       0
Bank Sta=178.9,198.8
XS Rating Curve= 0 ,0
Exp/Cntr(USF)=0,0
Exp/Cntr=0.3,0.1

Type RM Length L Ch R = 1 ,422     ,49.2,51.6,54.1
XS GIS Cut Line= 4
2122527.02710428356033.9021992892122486.91930496355807.460248955
2122467.70098445355776.5438203112122303.09189141355757.325499803
#Sta/Elev= 30
       0 2149.03    14.4 2146.35    67.8 2138.16    84.4 2134.52   106.4 2127.41
   124.4  2120.7   136.4 2117.13   154.4 2110.94     171 2108.41   194.4 2106.83
     211 2104.18   231.2 2104.82   236.5 2103.53   241.3 2101.86   250.8 2101.21
   254.4 2101.76   257.9 2103.44   262.1 2104.59   271.6 2105.56   284.8 2107.92
   304.6 2114.09   311.2 2115.51   317.8  2115.3   350.6 2117.18   390.5 2121.22
   397.1 2122.32   403.7 2122.24   420.2 2124.73   426.8 2125.27   432.1 2127.41
#Mann= 3 , 0 , 0
       0      .1       0   236.5    .045       0   257.9      .1       0
Bank Sta=236.5,257.9
XS Rating Curve= 0 ,0
Exp/Cntr(USF)=0,0
Exp/Cntr=0.3,0.1

Type RM Length L Ch R = 1 ,370     ,95.4,95.7,96
XS GIS Cut Line= 4
2122534.54731666356019.697353696 2122547.9165831355870.964264546
2122514.49341699 355729.751387772122349.04874479355754.818762346
#Sta/Elev= 30
       0 2144.97    19.8 2140.54      56 2130.68    69.2 2126.97   115.3 2112.28
   125.2 2109.98     145 2107.94   181.9 2106.59   205.5 2104.09   235.9 2104.59
   239.3 2104.17   241.2 2103.39     246 2101.51   252.7 2100.97   256.1 2101.21
   260.3 2103.18   262.9 2104.44   266.2 2104.91   290.3 2106.78   346.9 2105.98
     370  2106.4   387.2 2104.89   396.8 2104.68   403.4 2105.76   413.6  2110.3
   426.6 2113.72   430.5 2115.21   436.2  2116.3   453.2 2117.63   461.8 2118.84
#Mann= 3 , 0 , 0
       0      .1       0   241.2    .045       0   260.3      .1       0
Bank Sta=241.2,260.3
XS Rating Curve= 0 ,0
Exp/Cntr(USF)=0,0
Exp/Cntr=0.3,0.1

Type RM Length L Ch R = 1 ,274     ,27.7,26.7,25.6
XS GIS Cut Line= 5
2122584.68206581356046.4358865762122619.77639021355798.268878277
2122609.74944038  355739.77833762122523.68478767 355723.06675455
2122378.29401513355743.956233363
#Sta/Elev= 30
       0 2138.65    30.3 2129.56    43.6 2126.85      80 2117.18   119.8 2109.87
   150.7 2107.35   199.3 2107.02   229.1 2105.75   242.4 2104.62   262.3 2104.05
   265.7 2103.67     269 2102.53   272.3 2100.95   275.7 2100.67   282.3 2101.17
   285.32102.608   289.2 2103.59   295.6 2104.24     343  2104.3   373.1 2106.53
   389.7 2106.83   462.7 2105.29   482.6  2105.6   492.6 2104.65   505.8 2101.62
   509.1 2101.53   522.4 2102.94     529 2106.31     539 2109.08   544.5 2111.49
#Mann= 3 , 0 , 0
       0      .1       0     269    .045       0   285.3      .1       0
Bank Sta=269,285.3
XS Rating Curve= 0 ,0
Exp/Cntr(USF)=0,0
Exp/Cntr=0.3,0.1

Type RM Length L Ch R = 1 ,248     ,24,20.9,17.8
XS GIS Cut Line= 4
2122734.04441827356046.796939297  2122629.854919  355733.1968623
2122527.72857814355713.5968574882122356.14773298355745.437236437
#Sta/Elev= 30
       0 2116.96    25.1 2111.45    42.4 2109.27    66.6 2107.83   121.9 2106.09
   173.9 2106.13   208.4 2104.77   246.4  2104.9   270.6 2104.05     281 2104.62
   284.4 2104.24   289.62102.579   298.5 2100.58   301.7 2101.12   304.72102.727
   322.4 2104.11   367.2 2104.13   387.2 2104.86   407.3 2106.53   430.5 2106.58
   484.1  2104.9   524.1 2104.95   541.9 2103.04   550.3 2100.31   553.1 2100.07
   560.8 2100.39   564.1 2101.27   570.8 2104.35   587.5 2110.59     609 2113.65
#Mann= 3 , 0 , 0
       0      .1       0   289.6    .045       0   304.7      .1       0
#XS Ineff= 2 , 0
          192.53 2108.55
Permanent Ineff=
       F       F
Bank Sta=289.6,304.7
XS Rating Curve= 0 ,0
Exp/Cntr(USF)=0,0
Exp/Cntr=0.3,0.1