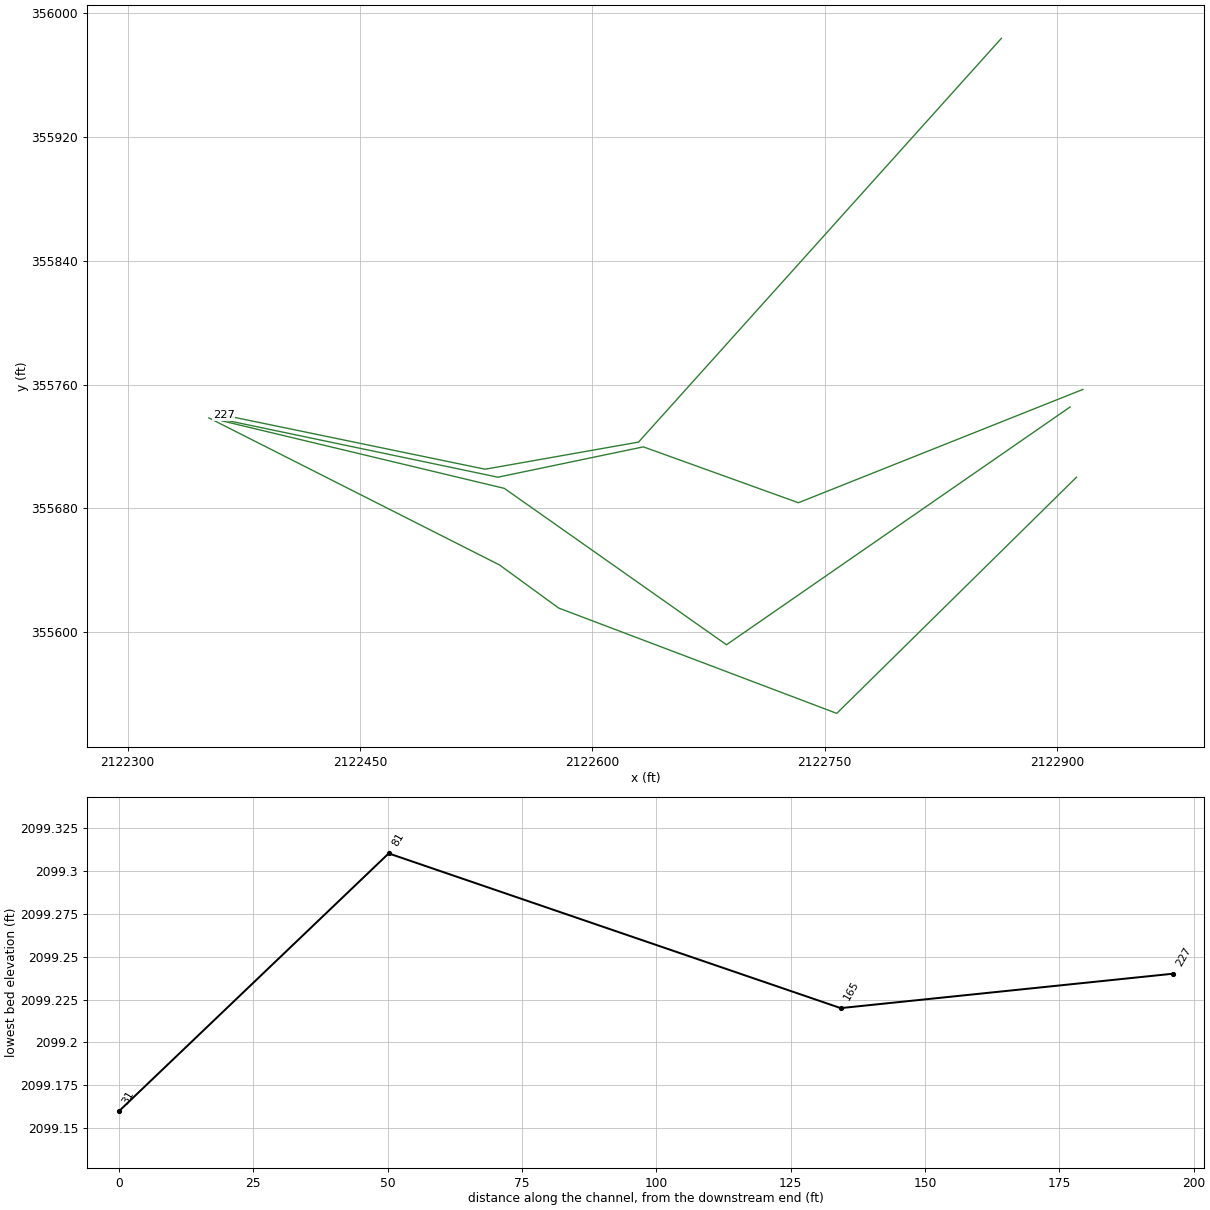
HEC-RAS study CLBRSNCKT3.prj: CLBRSNCKT3

--- CLBRSNCKT3.g01 (geometry) --- (continued)

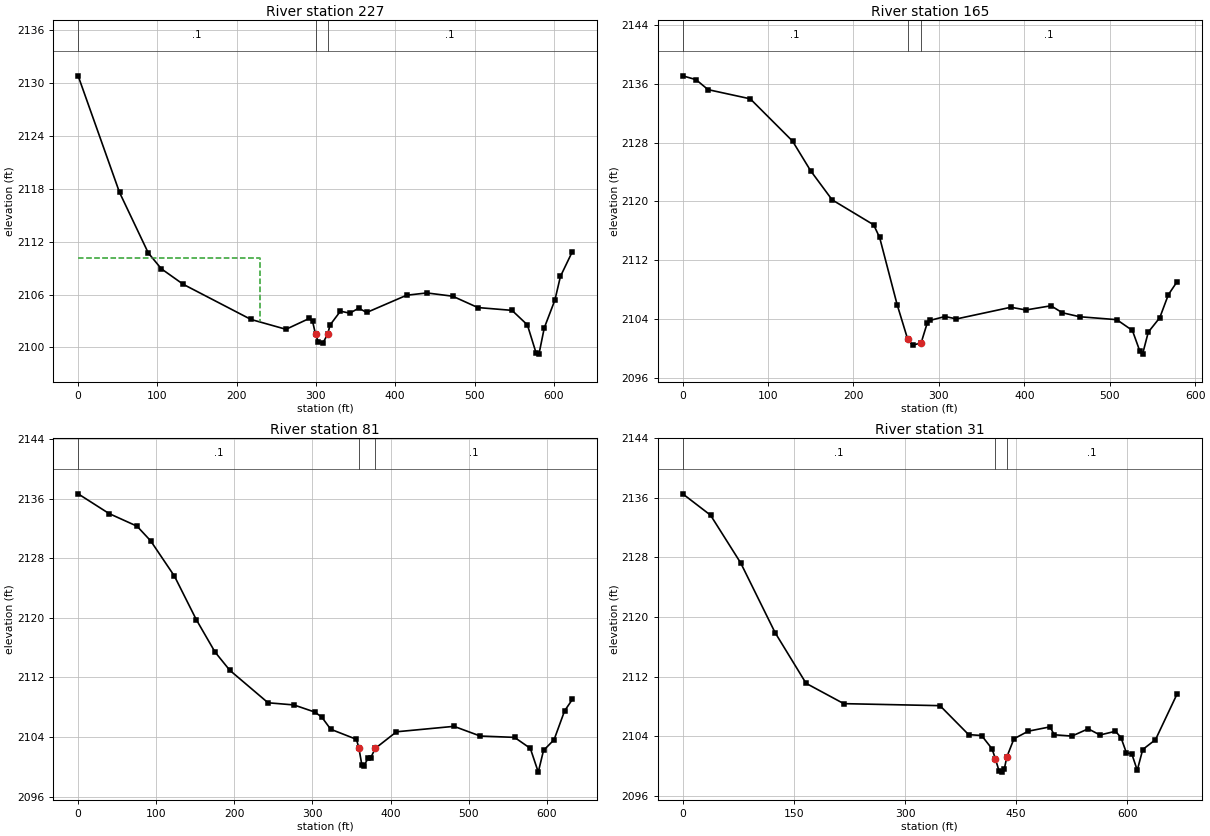
Type RM Length L Ch R = 1 ,227     ,70.9,61.8,52.7
XS GIS Cut Line= 4
2122864.02339755355983.870608058  2122629.854919355722.881070294
2122530.82331574355705.3442238832122362.19093876355740.279340434
#Sta/Elev= 30
       0 2130.85    52.2 2117.61    88.5 2110.73     105 2108.93   132.6 2107.17
     218 2103.18   262.2 2102.06   291.5 2103.29   295.7 2102.97   299.52101.492
   303.1 2100.61   308.9 2100.53   314.92101.525   317.7 2102.54   330.9 2104.12
   342.6 2103.89     354 2104.46     364 2103.97   414.4 2105.93   439.9 2106.19
   472.4 2105.82   504.2 2104.53   547.3 2104.21   566.7 2102.56   577.5 2099.42
   581.3 2099.24     588 2102.22   601.4 2105.38   608.4 2108.07   623.4 2110.88
#Mann= 3 , 0 , 0
       0      .1       0   299.5    .045       0   314.9      .1       0
#XS Ineff= 2 , 0
          230.02 2110.12
Permanent Ineff=
       F       F
Bank Sta=299.5,314.9
XS Rating Curve= 0 ,0
Exp/Cntr(USF)=0,0
Exp/Cntr=0.3,0.1

Type RM Length L Ch R = 1 ,165     ,85.8,84.1,82.4
XS GIS Cut Line= 5
2122916.63393678355756.9231839152122733.01283907355683.681060669
2122632.94965661355719.7863326922122539.07594935355700.186327879
2122364.11167431355736.884370801
#Sta/Elev= 30
       0  2137.1    15.6 2136.58    29.7 2135.22    79.1 2133.97   128.6 2128.22
   149.8 2124.18     175 2120.22   223.6 2116.82   230.6  2115.1   251.1 2105.96
   263.52101.233   269.3 2100.43   279.22100.757   286.4 2103.47   289.6 2103.81
   307.2 2104.34   320.6 2104.01   384.3  2105.6   401.9 2105.23   431.2  2105.8
   444.6 2104.85   464.8 2104.31   508.3 2103.91   526.6 2102.44   535.1 2099.69
   538.5 2099.22   545.2 2102.22   558.6 2104.17   568.7 2107.31   578.7 2109.04
#Mann= 3 , 0 , 0
       0      .1       0   263.5    .045       0   279.2      .1       0
Bank Sta=263.5,279.2
XS Rating Curve= 0 ,0
Exp/Cntr(USF)=0,0
Exp/Cntr=0.3,0.1

Type RM Length L Ch R = 1 ,81      ,50.8,50.2,49.6
XS GIS Cut Line= 4
2122908.38130318355745.5758127082122686.59177504355591.870511812
2122543.20226615355692.9652734752122361.02078328355736.595678515
#Sta/Elev= 30
       0 2136.63    39.5 2133.99    75.4 2132.29    92.8 2130.33   123.3 2125.59
   151.3 2119.75   175.2 2115.42   194.1 2112.97   243.1 2108.61   276.2 2108.32
   303.1 2107.36     312 2106.67   323.3 2105.06   356.2 2103.71   359.3 2102.59
   363.3  2100.2   365.6 2100.12   371.4 2101.21   374.6 2101.25   380.3 2102.49
   407.5 2104.72   481.1 2105.45   514.7 2104.15   558.6 2103.97   578.8  2102.5
     589 2099.31   595.7 2102.22   609.2 2103.65   622.7 2107.53   632.6 2109.05
#Mann= 3 , 0 , 0
       0      .1       0   359.3    .045       0   380.3      .1       0
Bank Sta=359.3,380.3
XS Rating Curve= 0 ,0
Exp/Cntr(USF)=0,0
Exp/Cntr=0.3,0.1

Type RM Length L Ch R = 1 ,31      ,31,31,31
XS GIS Cut Line= 5
2122912.50761998355700.1863278792122757.77073988355547.512606184
2122578.27595897355615.5968334262122540.10752855355643.449471844
2122352.47945739355738.516414063
#Sta/Elev= 30
       0 2136.55    37.6 2133.68    78.3 2127.26   124.7  2117.9   166.5 2111.09
   217.4 2108.36   347.2 2108.09   385.8  2104.2   403.3 2104.08   417.4  2102.3
   421.92100.966   426.8 2099.35   430.8 2099.16   433.9 2099.53   437.4  2101.2
     447 2103.64   466.3 2104.66   495.7 2105.24   501.3 2104.18   525.2    2104
   547.2 2104.98   563.1 2104.15     584 2104.65   591.4 2103.81   598.7 2101.77
   606.1 2101.59   613.4 2099.41   620.8  2102.2     638 2103.52   666.9 2109.61
#Mann= 3 , 0 , 0
       0      .1       0   421.9    .045       0   437.4      .1       0
Bank Sta=421.9,437.4
XS Rating Curve= 0 ,0
Exp/Cntr(USF)=0,0
Exp/Cntr=0.3,0.1
LCMann Table=0

Chan Stop Cuts=-1
Use User Specified Reach Order=0
Composite Channel Slope=5